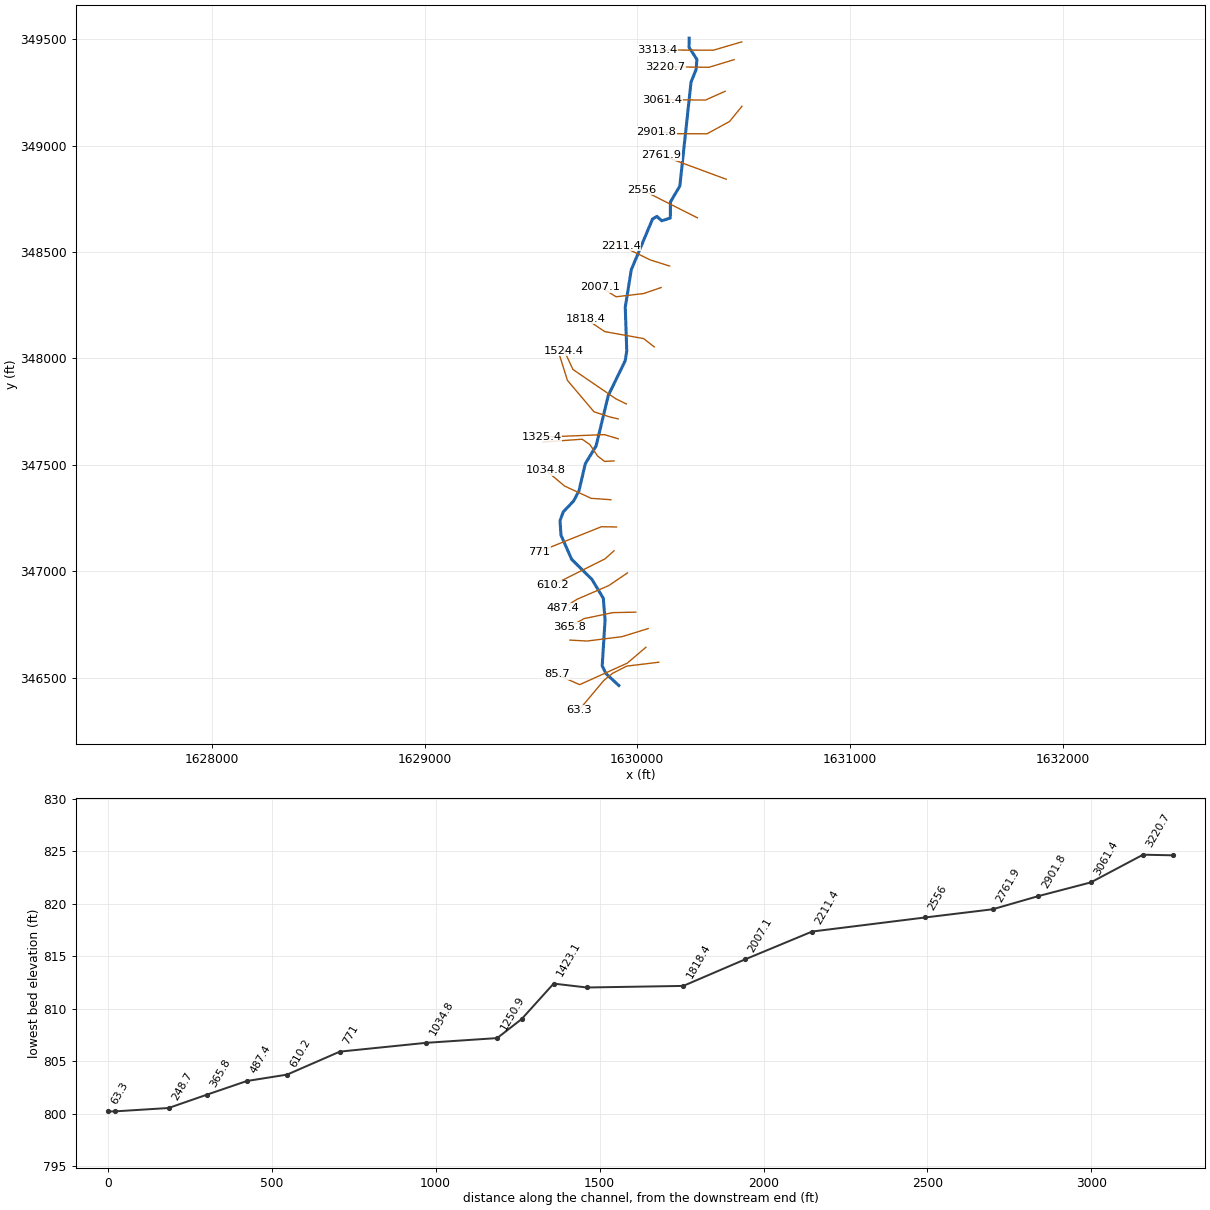
--- STKPOLRN.prj (project) ---

Proj Title=STKPOLRN
Current Plan=p01
Default Exp/Contr=0,0
English Units
Geom File=g01
Geom File=g02
Flow File=f01
Plan File=p01
BEGIN DESCRIPTION:
END DESCRIPTION:
DSS Export Rating Curves= 0
DSS Export Rating Curve Sorted= 0
DSS Export Volume Flow Curves= 0
DXF OffsetX= 0
DXF OffsetY= 0
DXF ScaleX= 0
DXF ScaleY= 0

--- STKPOLRN.p01 (plan) ---

Plan Title=Floodplain
Program Version=4.00
Geom File=g01
Flow File=f01
K Sum by GR=0
Std Step Tol=0.01
Critical Tol=0.01
Num of Std Step Trials=20
Max Error Tol=0.3
Flow Tol Ratio=0.001
Split Flow NTrial=30
Split Flow Tol=0.02
Split Flow Ratio=0.02
Log Output Level=0
Friction Slope Method=1
Unsteady Friction Slope Method=2
Unsteady Bridges Friction Slope Method=1
Global Log Level=0
CheckData=False
Run HTab=0
Run UNet=0
Run PostProcess=0
UNET Theta=0
UNET Theta Warmup=0
UNET ZTol=0
UNET ZSATol=0
UNET MxIter=0
UNET MaxInSteps=0
UNET DtIC=0
UNET DtMin=0
UNET MaxCRTS=0
UNET WFStab=0
UNET SFStab=0
UNET WFX=0
UNET SFX=0
UNET DSS MLevel=0
UNET DZMax Abort=0
UNET Convert EG Bridges=0
UNET Use Existing IB Tables=0
UNET Froude Limit=0
UNET Froude Power=0
Write IC File=0
Echo Input=False
Echo Output=False
Write Detailed=0

--- STKPOLRN.f01 (steady flow) ---

Flow Title=NFF Regression Equation
Program Version=4.10
Number of Profiles= 1
Profile Names=P100yr
River Rch & RM=STKPOLRN,Main            ,3313.4
1151.365
River Rch & RM=STKPOLRN,Main            ,771
1227.111
Boundary for River Rch & Prof#=STKPOLRN,Main            , 1
Up Type= 0
Dn Type= 3
Dn Slope=0.002
DSS Import GetInterval= 0
DSS Import GetPeak= 0
DSS Import FillOption= 0

--- STKPOLRN.g01 (geometry) ---

Geom Title=USGS 10m DEM
Program Version=4.10

River Reach=STKPOLRN        ,Main
Reach XY= 30
     1630244.048      349505.265     1630243.374       349462.05
     1630280.181      349405.854     1630276.301      349357.452
      1630252.75      349299.604     1630199.973      348810.021
     1630155.875      348735.715     1630155.253      348660.122
     1630114.889      348647.101     1630092.319      348667.717
     1630071.703      348655.348     1629971.908      348417.261
     1629943.491      348240.838     1629950.645      348034.779
     1629943.115      347988.956     1629863.692      347825.838
     1629806.396      347588.956     1629755.776       347505.47
     1629725.928      347378.018     1629700.645      347330.091
     1629652.287      347279.264     1629636.965      347238.072
     1629641.473      347169.579     1629691.549      347056.078
     1629787.125      346961.612      1629840.25      346873.524
     1629848.716      346771.927     1629835.194      346555.786
     1629852.555      346519.327     1629913.199      346463.308

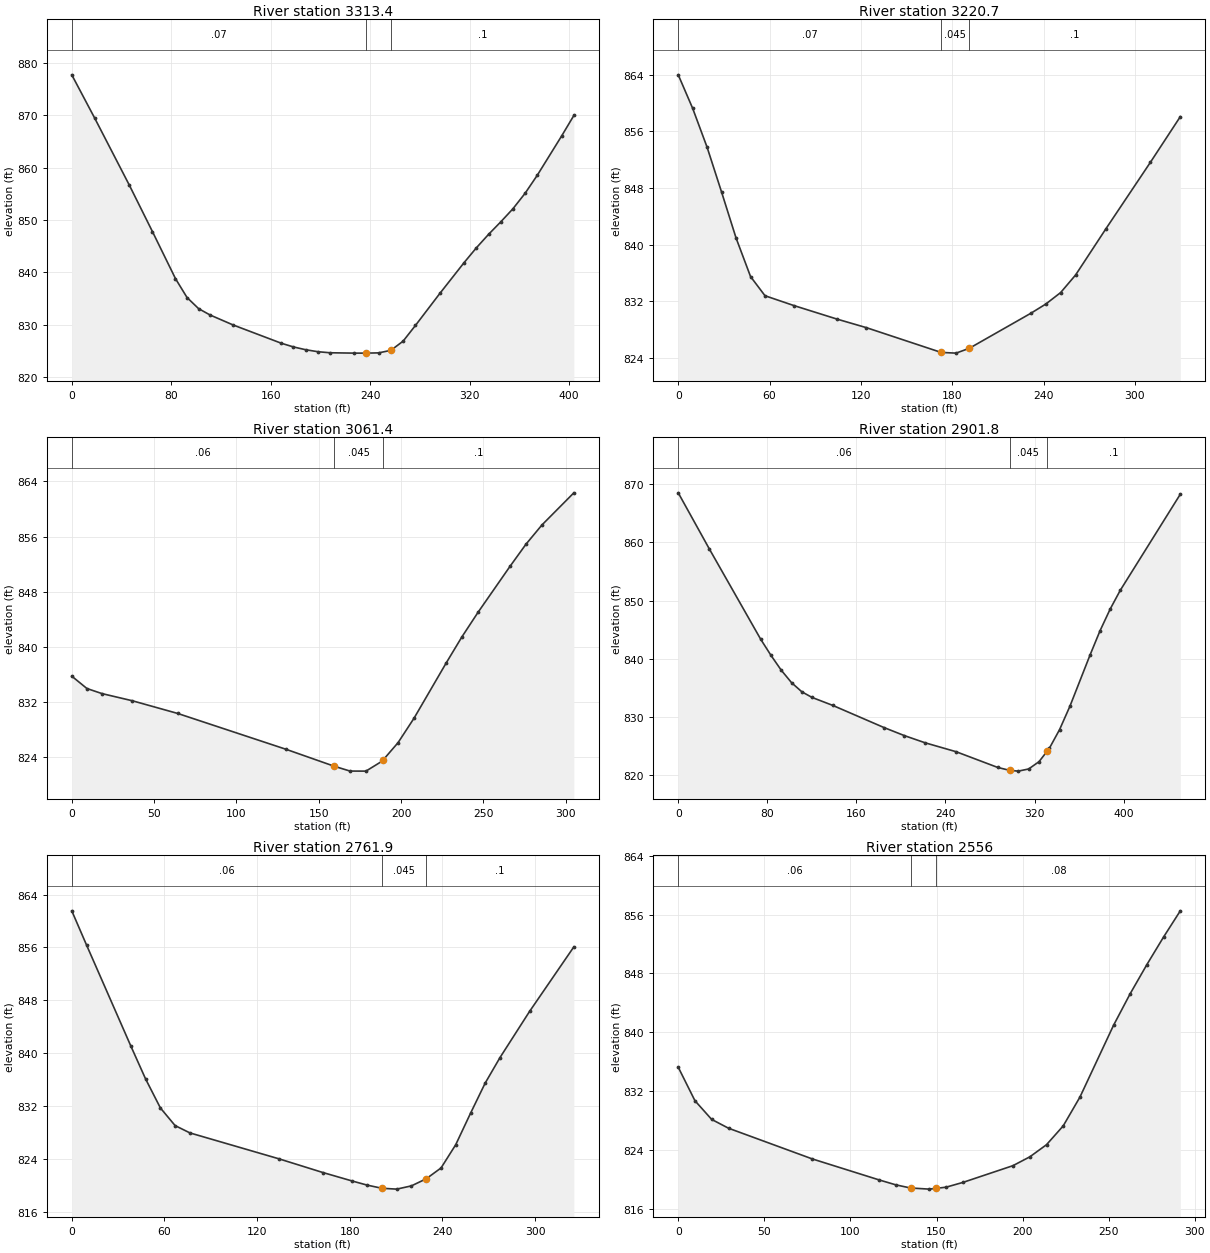
Type RM Length L Ch R = 1 ,3313.4  ,88.8,92.7,92.8
XS GIS Cut Line= 3
     1630490.928      349487.921     1630357.464      349448.858
     1630092.707      349449.943
#Sta/Elev= 30
       0   877.7    18.5  869.41    46.4   856.6    64.9  847.78    83.4  838.82
    92.7  835.21     102  833.09   111.2  831.88   129.8  829.97   168.5  826.49
   178.3  825.78   188.1  825.25   197.9  824.87   207.7  824.67   227.3   824.6
   236.8   824.6   246.9  824.65   256.7  825.14   266.5  826.89   276.4  829.88
     296  835.98   315.6  841.89   325.4  844.69   335.2  847.26     345  849.64
   354.8  852.14   364.6   855.1   374.4  858.54     394  866.04   403.8  869.94
#Mann= 3 , 0 , 0
       0     .07       0   236.8    .045       0   256.7      .1       0
Bank Sta=236.8,256.7
XS Rating Curve= 0 ,0
Exp/Cntr=0.3,0.1

Type RM Length L Ch R = 1 ,3220.7  ,159.1,159.4,159
XS GIS Cut Line= 3
      1630455.12       349404.37     1630336.848      349368.563
     1630130.685      349370.733
#Sta/Elev= 20
       0  863.99     9.5  859.24      19  853.73    28.5   847.4      38  840.92
    47.5  835.48      57  832.77      76  831.38   104.6  829.45   123.6  828.26
   172.7  824.76   182.5  824.66   191.2 825.342   231.6  830.29   241.4  831.59
   251.2  833.22     261   835.7   280.7  842.16   310.1  851.61   329.8  858.08
#Mann= 3 , 0 , 0
       0     .07       0   172.7    .045       0   191.2      .1       0
Bank Sta=172.7,191.2
XS Rating Curve= 0 ,0
Exp/Cntr=0.3,0.1

Type RM Length L Ch R = 1 ,3061.4  ,159.4,159.5,159.7
XS GIS Cut Line= 3
     1630412.803      349255.716     1630320.572      349214.483
     1630116.579      349216.653
#Sta/Elev= 20
       0  835.78     9.2  833.99    18.4  833.25    36.7  832.22    64.3  830.38
   130.2  825.18   159.3  822.74     169  822.03   178.7  822.02   188.5  823.46
   189.2823.6534   198.2  826.14   207.9  829.68   227.3  837.63     237  841.47
   246.8  845.03   266.2  851.68   275.9  854.89   285.6  857.68     305  862.34
#Mann= 3 , 0 , 0
       0     .06       0   159.3    .045       0   189.2      .1       0
Bank Sta=159.3,189.2
XS Rating Curve= 0 ,0
Exp/Cntr=0.3,0.1

Type RM Length L Ch R = 1 ,2901.8  ,148,139.9,132
XS GIS Cut Line= 5
     1630492.013      349185.186     1630433.419      349113.572
     1630328.167      349056.063     1630188.811      349056.542
     1630090.205      349066.314
#Sta/Elev= 27
       0   868.5    27.8  858.91      74  843.38    83.3  840.59    92.5  838.05
   101.8   835.9     111  834.34   120.2  833.37   138.7  832.01   184.8   828.2
   203.2  826.81   221.8  825.58   249.6  824.05   286.8  821.36   297.6820.8538
   305.4  820.72   314.7  821.09     324  822.34   331.2824.1165   333.2  824.61
   342.5  827.86   351.8  831.88   369.8  840.64   378.8  844.82   387.9  848.54
   396.9  851.74   450.9  868.26
#Mann= 3 , 0 , 0
       0     .06       0   297.6    .045       0   331.2      .1       0
Bank Sta=297.6,331.2
XS Rating Curve= 0 ,0
Exp/Cntr=0.3,0.1

Type RM Length L Ch R = 1 ,2761.9  ,208.4,205.9,202.7
XS GIS Cut Line= 2
     1630418.228      348842.304     1630113.323      348955.152
#Sta/Elev= 22
       0  861.54     9.6  856.35    38.2  841.12    47.8  836.12    57.4  831.73
    66.9  829.07    76.5  827.96   133.9  824.06   162.6  821.97   181.7  820.68
   191.2  820.07   200.8  819.59   210.4  819.46   219.9  819.95   229.5  821.02
   239.1  822.66   248.6  826.17   258.2  830.93   267.7   835.5   277.3  839.36
   296.4  846.32   325.1  856.09
#Mann= 3 , 0 , 0
       0     .06       0   200.8    .045       0   229.5      .1       0
Bank Sta=200.8,229.5
XS Rating Curve= 0 ,0
Exp/Cntr=0.3,0.1

Type RM Length L Ch R = 1 ,2556    ,337.9,344.6,342.1
XS GIS Cut Line= 2
     1630282.594      348661.098     1630022.178      348792.391
#Sta/Elev= 22
       0  835.25     9.7   830.7    19.4  828.16    29.2  826.96    77.8  822.79
   116.7  819.93   126.4  819.26   134.9 818.835   145.8  818.68   149.9 818.791
   155.5  818.94   165.3  819.59   194.4  821.87   204.2  823.07   213.9  824.72
   223.6  827.28   233.3  831.19   252.8  840.94   262.5  845.25   272.2  849.21
   281.9  852.96   291.6  856.51
#Mann= 3 , 0 , 0
       0     .06       0   134.9    .045       0   149.9     .08       0
Bank Sta=134.9,149.9
XS Rating Curve= 0 ,0
Exp/Cntr=0.3,0.1

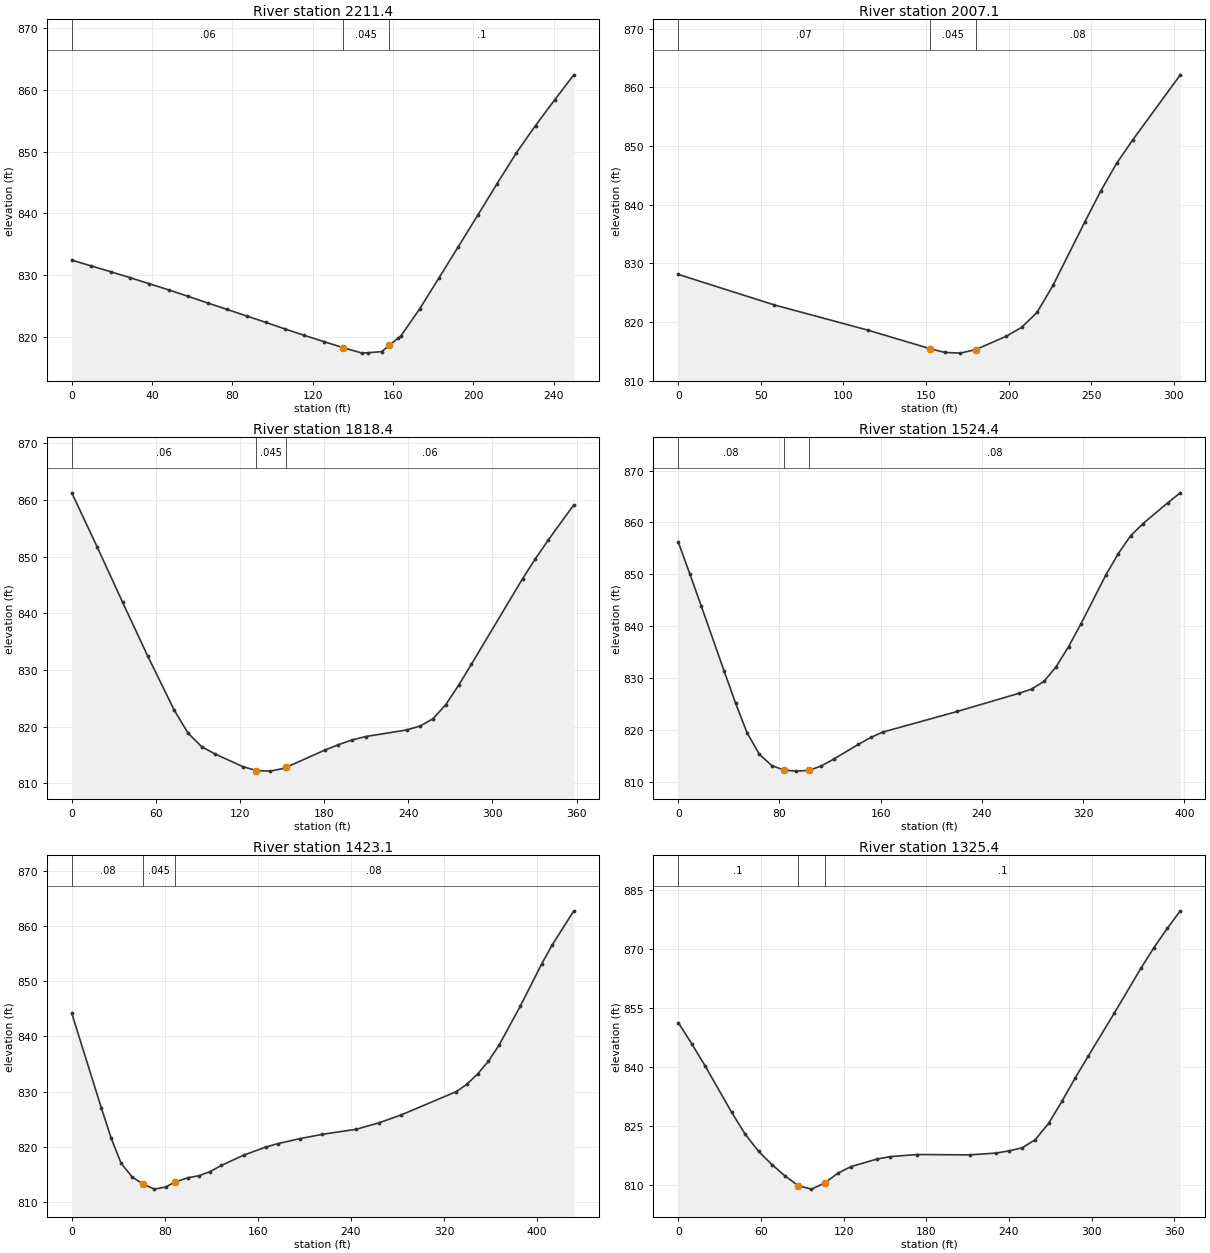
Type RM Length L Ch R = 1 ,2211.4  ,191.1,204.3,217
XS GIS Cut Line= 3
     1630152.386      348434.318     1630060.155      348463.615
     1629922.351      348530.889
#Sta/Elev= 30
       0  832.42     9.7  831.48    19.4  830.54      29  829.58    38.7  828.58
    48.4  827.58    58.1  826.53    67.7  825.47    77.4  824.42    87.1  823.36
    96.8  822.31   106.4  821.24   115.9  820.21   125.5  819.22   135.1  818.23
   144.7  817.34   147.6  817.41   154.3  817.58   158.1818.5827   162.6  819.77
   163.9  820.11   173.4  824.56     183  829.58   192.6  834.62   202.2  839.69
   211.8  844.79   221.4  849.77     231  854.24   240.5  858.38   250.1  862.46
#Mann= 3 , 0 , 0
       0     .06       0   135.1    .045       0   158.1      .1       0
Bank Sta=135.1,158.1
XS Rating Curve= 0 ,0
Exp/Cntr=0.3,0.1

Type RM Length L Ch R = 1 ,2007.1  ,195.5,188.7,182
XS GIS Cut Line= 4
     1630112.238      348333.407     1630029.773      348305.195
      1629900.65      348290.004     1629826.865      348335.577
#Sta/Elev= 16
       0  828.11    58.1  822.91     115  818.59   152.2  815.46   161.4  814.81
   170.7  814.69     180  815.29   198.6  817.57   207.9  819.09   217.2  821.64
   226.8  826.22   246.1  837.05   255.7   842.3   265.4  847.06     275  850.99
   303.9  862.12
#Mann= 3 , 0 , 0
       0     .07       0   152.2    .045       0     180     .08       0
Bank Sta=152.2,180
XS Rating Curve= 0 ,0
Exp/Cntr=0.3,0.1

Type RM Length L Ch R = 1 ,1818.4  ,303.8,294,284.3
XS GIS Cut Line= 4
     1630079.686      348054.544     1630029.773      348093.606
     1629847.481      348126.159     1629756.336      348186.922
#Sta/Elev= 27
       0  861.25    18.1  851.72    36.2  841.98    54.3   832.4    73.1   822.9
    82.9  818.88    92.6  816.48   102.4  815.16   121.9  812.97   131.6  812.27
   141.4  812.16   151.1  812.64     153  812.84   180.3  815.85   190.1  816.82
   199.8  817.65   209.6  818.26   238.8  819.42   248.6  820.13   257.7  821.41
   266.8  823.91   275.9   827.3   285.1  831.04   321.6  846.13   330.7  849.63
   339.8  852.91   358.1  859.14
#Mann= 3 , 0 , 0
       0     .06       0   131.6    .045       0     153     .06       0
Bank Sta=131.6,153
XS Rating Curve= 0 ,0
Exp/Cntr=0.3,0.1

Type RM Length L Ch R = 1 ,1524.4  ,94.4,101.3,107.4
XS GIS Cut Line= 4
     1629948.393      347786.532     1629899.565      347810.403
     1629697.742      347948.207     1629656.509      348037.183
#Sta/Elev= 29
       0  856.21     9.1   850.1    18.1  843.93    36.2  831.37    45.3  825.14
    54.4   819.4    64.1  815.27    73.9  813.09    83.7  812.21    93.4  812.01
   103.2  812.15     113     813   122.8  814.32   142.3  817.16   152.1   818.5
   161.9  819.56   220.5  823.52   269.4  827.03   279.2  827.83     289  829.31
   298.7  832.17   308.5  836.04   318.4  840.49     338  849.87   347.8  853.98
   357.6  857.45   367.4  859.77     387  863.81   396.8   865.7
#Mann= 3 , 0 , 0
       0     .08       0    83.7    .045       0   103.2     .08       0
Bank Sta=83.7,103.2
XS Rating Curve= 0 ,0
Exp/Cntr=0.3,0.1

Type RM Length L Ch R = 1 ,1423.1  ,89.5,97.7,105.8
XS GIS Cut Line= 5
     1629910.415      347716.002     1629869.183      347725.768
     1629796.483      347749.639       1629671.7      347897.209
     1629635.893      348011.141
#Sta/Elev= 30
       0  844.19    25.4  827.09    33.9  821.59    42.4  817.07    51.9  814.58
    61.5  813.28    71.1  812.38    80.6  812.76    88.4 813.629    99.8  814.44
   109.3   814.8   118.9  815.56   128.6  816.67   147.9  818.54   167.2  820.02
   176.9   820.6   196.2  821.52   215.5   822.3   244.5  823.21   263.8  824.36
   283.2  825.81   330.5  830.02   339.7  831.37   348.9  833.23   358.1   835.5
   367.3  838.44   385.6   845.5     404  853.16   413.2  856.64   431.6  862.74
#Mann= 3 , 0 , 0
       0     .08       0    61.5    .045       0    88.4     .08       0
Bank Sta=61.5,88.4
XS Rating Curve= 0 ,0
Exp/Cntr=0.3,0.1

Type RM Length L Ch R = 1 ,1325.4  ,97.8,74.6,51.2
XS GIS Cut Line= 3
     1629910.415      347622.686     1629845.311      347642.218
     1629549.087      347630.282
#Sta/Elev= 30
       0  851.26     9.7  845.93    19.4  840.34    38.8  828.47    48.6  822.94
    58.3   818.6      68  815.23    77.5  812.35    87.1  809.87    96.7     809
   106.2  810.52   115.8  813.03   125.4  814.72   144.5  816.65     154  817.25
   173.2  817.78   211.4  817.69   230.6  818.15   240.1   818.7   249.7   819.5
   259.2  821.56   268.8  825.68   278.4  831.23   287.9  837.08   297.5  842.71
   316.6  853.71   335.7  864.98   345.3  870.29   354.9  875.13   364.4   879.6
#Mann= 3 , 0 , 0
       0      .1       0    87.1    .045       0   106.2      .1       0
Bank Sta=87.1,106.2
XS Rating Curve= 0 ,0
Exp/Cntr=0.3,0.1

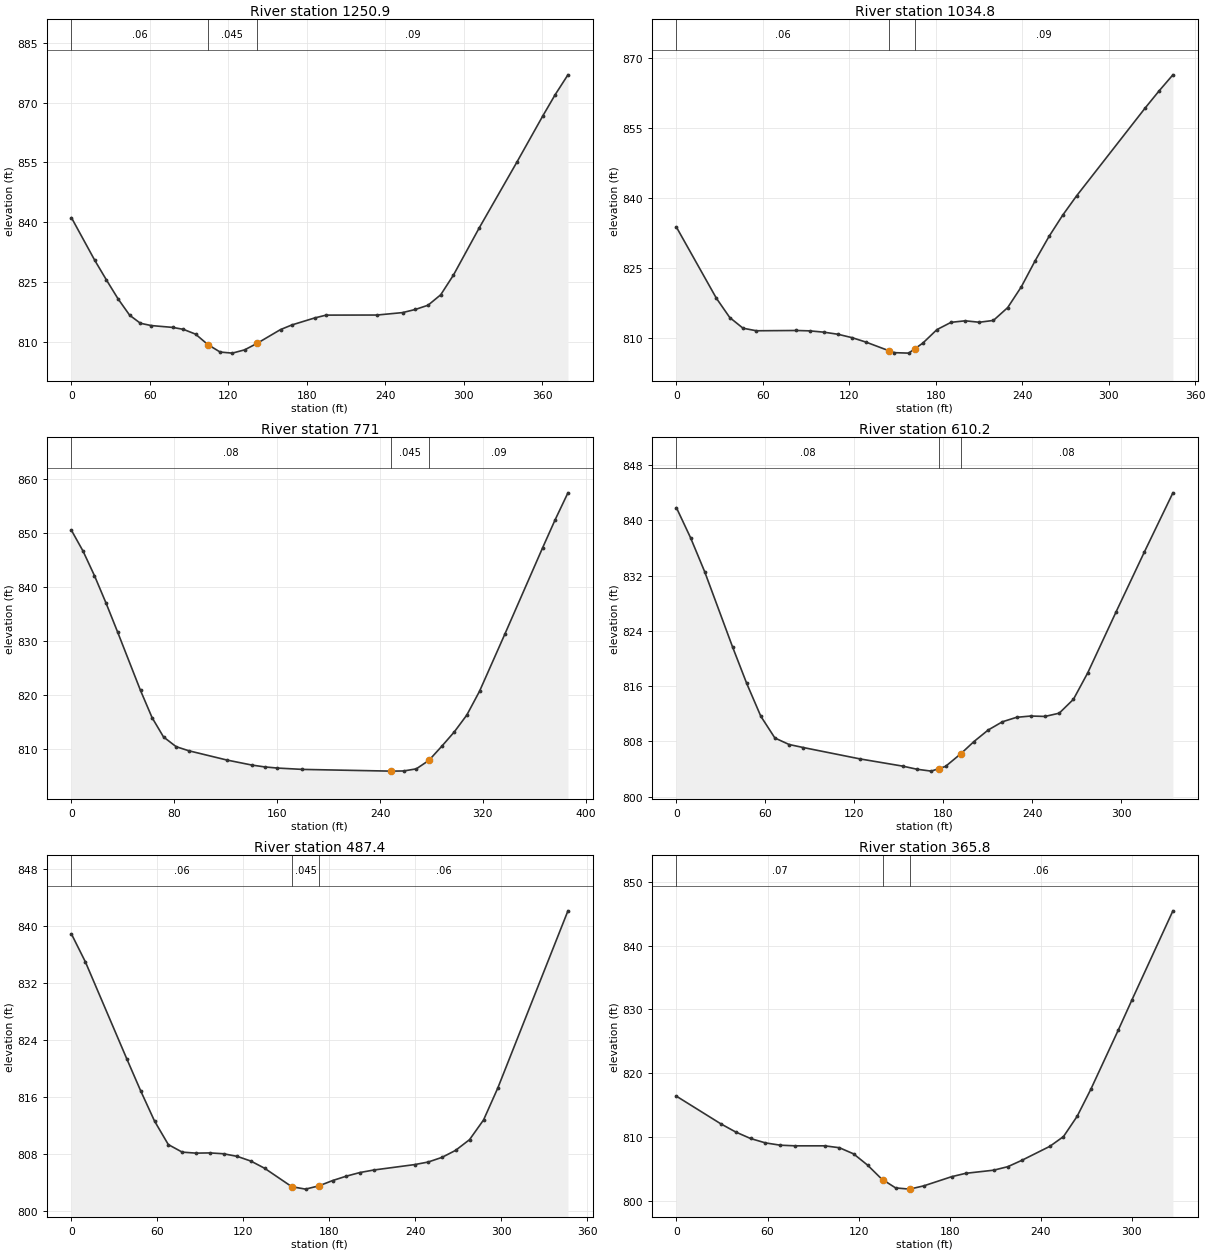
Type RM Length L Ch R = 1 ,1250.9  ,203.4,216.1,228.3
XS GIS Cut Line= 6
     1629890.884       347518.52     1629846.396      347516.349
     1629813.844      347541.306     1629776.952       347595.56
     1629741.145      347620.516     1629556.683      347607.495
#Sta/Elev= 30
       0  841.13    17.8  830.46    26.7  825.55    35.6  820.81    44.5  816.69
    52.7  814.68      61   814.1    77.4  813.64    85.6  813.15    94.9  811.95
   104.3  809.33   113.7  807.46     123  807.19   132.4  808.01   141.8  809.61
   159.9   813.1   168.6  814.26   186.1  816.02   194.8  816.72   233.7  816.74
   253.2  817.35   262.9  818.13   272.7   819.2   282.4  821.82   292.1  826.74
   311.6  838.44   340.8  855.16   360.3  866.56     370  872.02   379.7  876.96
#Mann= 3 , 0 , 0
       0     .06       0   104.3    .045       0   141.8     .09       0
Bank Sta=104.3,141.8
XS Rating Curve= 0 ,0
Exp/Cntr=0.3,0.1

Type RM Length L Ch R = 1 ,1034.8  ,245,263.8,281.9
XS GIS Cut Line= 4
     1629875.693      347336.228     1629783.462      347342.738
     1629658.679      347400.247     1629570.789      347474.032
#Sta/Elev= 30
       0  833.78    27.7  818.53      37  814.38    46.2  812.09    55.5  811.54
    83.2   811.6    92.5  811.52   102.3  811.24   112.1  810.79   121.9  810.06
   131.7  809.09   147.6807.2402   151.3  806.84   161.2  806.74  165.23807.6251
     171  808.89   180.8  811.79   190.6  813.35   200.4  813.68   210.2  813.37
     220  813.76   229.9  816.51   239.4  820.99     249  826.59   258.6  831.79
   268.1  836.36   277.7  840.49   325.5  859.43     335  863.04   344.6  866.49
#Mann= 3 , 0 , 0
       0     .06       0   147.6    .045       0  165.23     .09       0
Bank Sta=147.6,165.23
XS Rating Curve= 0 ,0
Exp/Cntr=0.3,0.1

Type RM Length L Ch R = 1 ,771     ,159,160.8,162.4
XS GIS Cut Line= 3
      1629902.82       347208.19     1629831.205      347209.275
     1629539.322      347092.087
#Sta/Elev= 27
       0   850.5       9  846.66    17.9   842.1    26.9  837.02    35.8  831.72
    53.7  820.84    62.7  815.81    71.6  812.23    81.4  810.43    91.3  809.67
   120.8  807.96   140.4  807.02   150.3  806.68   160.1  806.47   179.7  806.22
   248.6   805.9   258.4  805.93   268.2  806.32     278  807.88   287.9  810.47
   297.7  813.14   307.5  816.28   317.4  820.69     337  831.22   366.5  847.28
   376.3   852.5   386.2  857.46
#Mann= 3 , 0 , 0
       0     .08       0   248.6    .045       0     278     .09       0
Bank Sta=248.6,278
XS Rating Curve= 0 ,0
Exp/Cntr=0.3,0.1

Type RM Length L Ch R = 1 ,610.2   ,124,122.9,121.5
XS GIS Cut Line= 3
     1629890.884      347096.428     1629848.567       347058.45
     1629600.086      346933.667
#Sta/Elev= 28
       0   841.8     9.5  837.47      19  832.57    37.9  821.64    47.4  816.39
    56.9  811.65    66.4   808.5      76  807.56    85.6  807.12     124  805.47
   152.7  804.43   162.3  803.98   171.9  803.71   176.8804.0598   181.5  804.39
   191.8806.2193   200.7  807.99   210.3  809.66   219.9  810.85   229.4  811.49
     239  811.68   248.6  811.62   258.2  812.09   267.8   814.1   277.4  817.91
   296.6  826.76   315.7  835.43   334.9  843.96
#Mann= 3 , 0 , 0
       0     .08       0   176.8    .045       0   191.8     .08       0
Bank Sta=176.8,191.8
XS Rating Curve= 0 ,0
Exp/Cntr=0.3,0.1

Type RM Length L Ch R = 1 ,487.4   ,126,121.6,116.3
XS GIS Cut Line= 4
     1629953.818      346992.261     1629865.928      346932.582
     1629717.273      346868.563     1629651.084      346826.245
#Sta/Elev= 28
       0  838.88     9.7  834.98    38.6  821.38    48.3  816.89      58  812.64
    67.6  809.35    77.3  808.29    86.9  808.15    96.6  808.18   106.2  808.06
   115.8  807.69   125.3  807.03   134.8  806.03   153.8  803.44   163.4   803.1
   172.9  803.57   182.4  804.31   191.9  804.92   201.4  805.43     211  805.78
   239.5  806.54     249   806.9   258.6  807.55   268.1  808.53   277.9  810.04
   287.7  812.81   297.6  817.27   346.6  842.14
#Mann= 3 , 0 , 0
       0     .06       0   153.8    .045       0   172.9     .06       0
Bank Sta=153.8,172.9
XS Rating Curve= 0 ,0
Exp/Cntr=0.3,0.1

Type RM Length L Ch R = 1 ,365.8   ,118.4,117,114.9
XS GIS Cut Line= 4
     1629992.881      346807.799     1629885.459      346805.629
     1629749.825      346777.417     1629679.296       346737.27
#Sta/Elev= 28
       0  816.37    29.3  812.03    39.1  810.75    48.8  809.74    58.6  809.05
    68.4  808.69    78.1  808.59    97.7  808.59   107.4  808.29   116.7  807.33
   125.9  805.57   135.2  803.39   136.2803.2377   144.4  801.99   153.6   801.8
   162.9  802.31   181.3  803.75   190.6  804.28     209  804.77   218.3  805.32
   227.5  806.31     246  808.51     255  810.04     264  813.22     273  817.45
   291.1  826.74   300.1  831.47   327.1  845.44
#Mann= 3 , 0 , 0
       0     .07       0   136.2    .045       0   153.6     .06       0
Bank Sta=136.2,153.6
XS Rating Curve= 0 ,0
Exp/Cntr=0.3,0.1

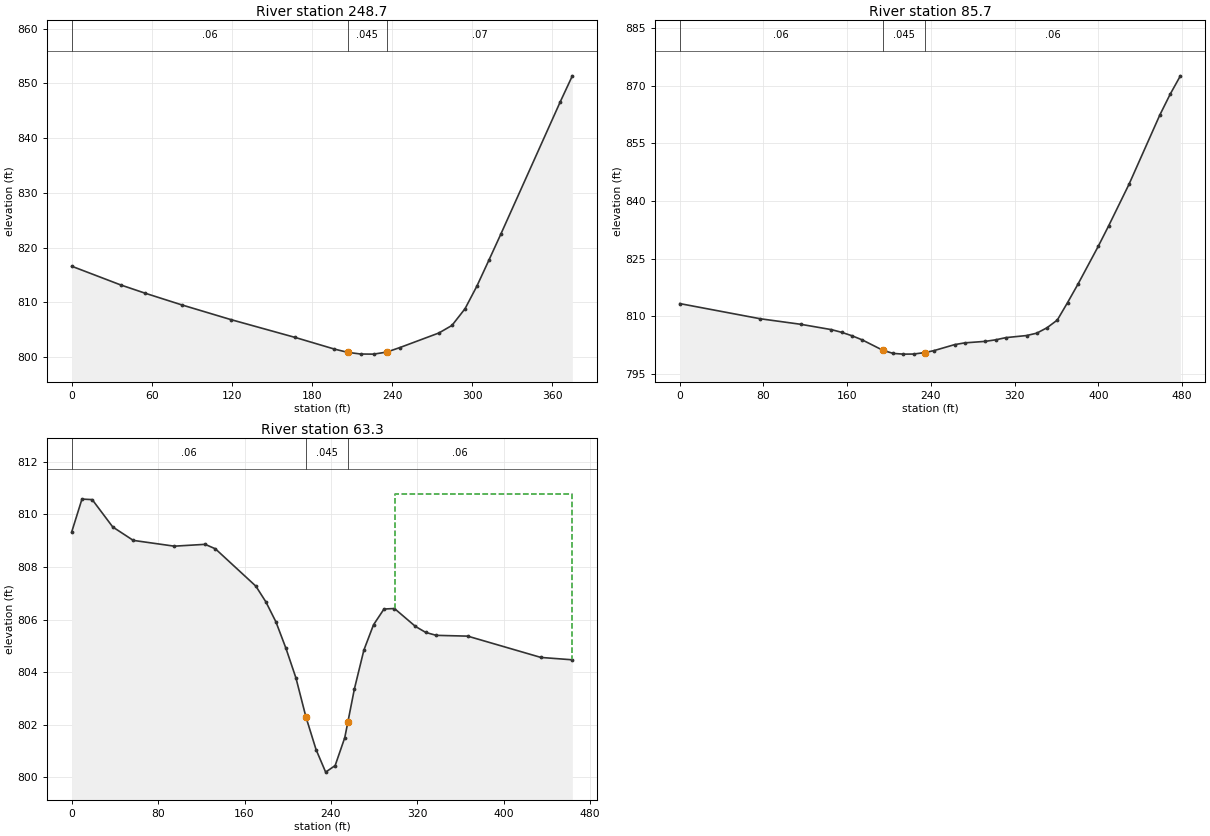
Type RM Length L Ch R = 1 ,248.7   ,156.5,163,170
XS GIS Cut Line= 4
     1630051.475      346730.759     1629928.862      346692.782
     1629763.931      346672.165     1629683.636      346676.506
#Sta/Elev= 20
       0  816.59    36.7  813.17      55  811.66    82.5  809.52   119.2  806.84
   167.5  803.57   196.8  801.45   206.6  800.86   216.4  800.55   226.1  800.53
   235.9   800.9   245.7  801.72     275  804.39   284.8  805.77   294.6  808.82
   303.5  812.96   312.4  817.65   321.4  822.44     366  846.66     375  851.37
#Mann= 3 , 0 , 0
       0     .06       0   206.6    .045       0   235.9     .07       0
Bank Sta=206.6,235.9
XS Rating Curve= 0 ,0
Exp/Cntr=0.3,0.1

Type RM Length L Ch R = 1 ,85.7    ,16.3,22.4,28.3
XS GIS Cut Line= 4
     1630040.624      346642.869     1629952.733      346567.999
     1629729.209      346467.087     1629621.787       346514.83
#Sta/Elev= 30
       0  813.35      77   809.4   115.5  807.97   144.9  806.58   154.7  805.88
   164.5  804.99   174.3  803.92   193.9  801.23   203.8   800.4   213.6  800.21
   223.4  800.23   234.5  800.63     243  801.13   262.6  802.68   272.4  803.14
     292  803.53   301.8  803.93   311.6   804.5   331.3  805.04   341.1  805.66
   350.9  807.07   360.7  809.06   370.5   813.6   380.3  818.32   399.9  828.27
   409.7  833.52   429.3  844.41   458.7  862.39   468.5  867.75   478.3  872.55
#Mann= 3 , 0 , 0
       0     .06       0   193.9    .045       0   234.5     .06       0
Bank Sta=193.9,234.5
XS Rating Curve= 0 ,0
Exp/Cntr=0.3,0.1

Type RM Length L Ch R = 1 ,63.3    ,60.1,63.3,66.5
XS GIS Cut Line= 5
     1630101.062      346572.556     1629950.238       346554.11
     1629884.048      346520.473     1629842.816      346486.836
     1629724.543      346345.777
#Sta/Elev= 30
       0  809.33     9.5  810.58      19  810.56      38  809.52      57  809.01
      95  808.79   123.5  808.86     133  808.69   170.5  807.27   179.8  806.67
   189.1  805.91   198.4   804.9   207.6  803.78   216.9  802.29   226.2  801.06
   235.1   800.2   243.9  800.45   252.8  801.51   255.7  802.11   261.7  803.36
   270.5  804.84   279.4   805.8   289.1   806.4   298.8  806.42   318.2  805.74
   327.8  805.51   337.5   805.4   366.6  805.37   434.4  804.56   463.5  804.47
#Mann= 3 , 0 , 0
       0     .06       0   216.9    .045       0   255.7     .06       0
#XS Ineff= 2 , 0
                          298.87          810.78
Permanent Ineff=
       F       F
Bank Sta=216.9,255.7
XS Rating Curve= 0 ,0
Exp/Cntr=0.3,0.1

Chan Stop Cuts=-1
Use User Specified Reach Order=0
Composite Channel Slope=5

--- STKPOLRN.g02 (geometry) ---

Geom Title=USGS 10m DEM_old
Program Version=4.10

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
River Reach=STKPOLRN        ,Main
Reach XY= 30
     1630244.048      349505.265     1630237.357      349474.106
     1630273.523      349424.119     1630276.301      349357.452
     1630250.667      349311.283     1630192.273      348794.257
     1630154.079      348736.619     1630154.079      348659.535
     1630108.245      348649.119     1630095.051      348671.341
      1630083.94      348663.007     1629969.742      348418.459
     1629941.964      348232.695     1629947.173      348000.056
     1629849.951      347798.841     1629806.548      347593.112
     1629759.673      347518.459     1629728.423      347371.758
     1629633.929      347258.928     1629628.596      347230.264
     1629632.937      347151.272     1629652.902      347112.209
     1629745.784      346988.077     1629787.451      346956.827
     1629838.666      346877.834     1629851.687      346752.834
     1629834.129      346658.295     1629835.194      346555.786
     1629852.555      346519.327     1629913.199      346463.308

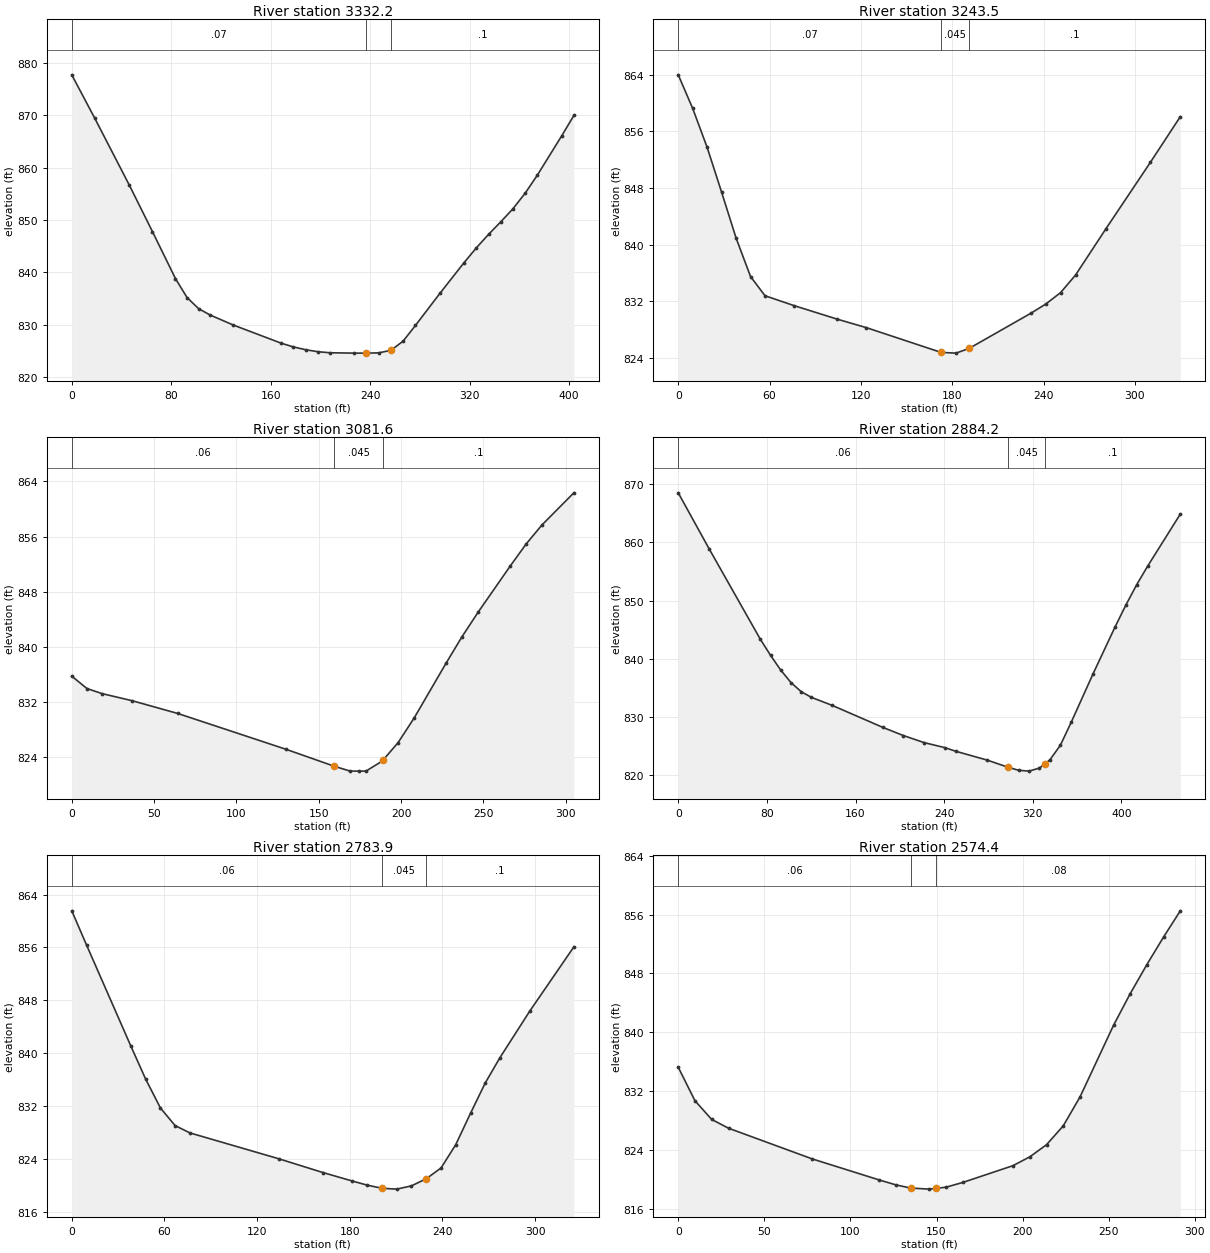
Type RM Length L Ch R = 1 ,3332.2  ,87.9,88.7,89.3
XS GIS Cut Line= 3
     1630490.928      349487.921     1630357.464      349448.858
     1630092.707      349449.943
#Sta/Elev= 30
       0   877.7    18.5  869.41    46.4   856.6    64.9  847.78    83.4  838.82
    92.7  835.21     102  833.09   111.2  831.88   129.8  829.97   168.5  826.49
   178.3  825.78   188.1  825.25   197.9  824.87   207.7  824.67   227.3   824.6
   236.8   824.6   246.9  824.65   256.7  825.14   266.5  826.89   276.4  829.88
     296  835.98   315.6  841.89   325.4  844.69   335.2  847.26     345  849.64
   354.8  852.14   364.6   855.1   374.4  858.54     394  866.04   403.8  869.94
#Mann= 3 , 0 , 0
       0     .07       0   236.8    .045       0   256.7      .1       0
Bank Sta=236.8,256.7
XS Rating Curve= 0 ,0
Exp/Cntr=0.3,0.1

Type RM Length L Ch R = 1 ,3243.5  ,161.4,161.9,162.4
XS GIS Cut Line= 3
      1630455.12       349404.37     1630336.848      349368.563
     1630130.685      349370.733
#Sta/Elev= 20
       0  863.99     9.5  859.24      19  853.73    28.5   847.4      38  840.92
    47.5  835.48      57  832.77      76  831.38   104.6  829.45   123.6  828.26
   172.7  824.76   182.5  824.66   191.2  825.34   231.6  830.29   241.4  831.59
   251.2  833.22     261   835.7   280.7  842.16   310.1  851.61   329.8  858.08
#Mann= 3 , 0 , 0
       0     .07       0   172.7    .045       0   191.2      .1       0
Bank Sta=172.7,191.2
XS Rating Curve= 0 ,0
Exp/Cntr=0.3,0.1

Type RM Length L Ch R = 1 ,3081.6  ,188.9,197.4,204.2
XS GIS Cut Line= 3
     1630412.803      349255.716     1630320.572      349214.483
     1630116.579      349216.653
#Sta/Elev= 21
       0  835.78     9.2  833.99    18.4  833.25    36.7  832.22    64.3  830.38
   130.2  825.18   159.3  822.74     169  822.03   174.2  822.02   178.7  822.02
   188.5  823.46   189.2  823.65   198.2  826.14   207.9  829.68   227.3  837.63
     237  841.47   246.8  845.03   266.2  851.68   275.9  854.89   285.6  857.68
     305  862.34
#Mann= 3 , 0 , 0
       0     .06       0   159.3    .045       0   189.2      .1       0
Bank Sta=159.3,189.2
XS Rating Curve= 0 ,0
Exp/Cntr=0.3,0.1

Type RM Length L Ch R = 1 ,2884.2  ,116.5,100.3,85.7
XS GIS Cut Line= 5
     1630492.013      349185.186     1630433.419      349113.572
     1630328.167      349056.063     1630203.384      349011.575
     1630097.047      349031.106
#Sta/Elev= 29
       0   868.5    27.8  858.91      74  843.38    83.3  840.59    92.5  838.05
   101.8   835.9     111  834.34   120.2  833.37   138.7  832.01   184.8   828.2
   203.2  826.81   221.9   825.6   240.9  824.72   250.3  824.12   278.7   822.6
   297.6  821.37   307.1  820.85   316.6   820.7     326  821.23   331.2  822.01
   335.5  822.66   344.9  825.16   354.8  829.16   374.4  837.43   394.1  845.42
   403.9   849.2   413.8  852.74   423.6   855.9   453.1  864.85
#Mann= 3 , 0 , 0
       0     .06       0   297.6    .045       0   331.2      .1       0
Bank Sta=297.6,331.2
XS Rating Curve= 0 ,0
Exp/Cntr=0.3,0.1

Type RM Length L Ch R = 1 ,2783.9  ,213,209.5,205.5
XS GIS Cut Line= 2
     1630418.228      348842.304     1630113.323      348955.152
#Sta/Elev= 22
       0  861.54     9.6  856.35    38.2  841.12    47.8  836.12    57.4  831.73
    66.9  829.07    76.5  827.96   133.9  824.06   162.6  821.97   181.7  820.68
   191.2  820.07   200.8  819.59   210.4  819.46   219.9  819.95   229.5  821.02
   239.1  822.66   248.6  826.17   258.2  830.93   267.7   835.5   277.3  839.36
   296.4  846.32   325.1  856.09
#Mann= 3 , 0 , 0
       0     .06       0   200.8    .045       0   229.5      .1       0
Bank Sta=200.8,229.5
XS Rating Curve= 0 ,0
Exp/Cntr=0.3,0.1

Type RM Length L Ch R = 1 ,2574.4  ,350.1,346,348.3
XS GIS Cut Line= 2
     1630282.594      348661.098     1630022.178      348792.391
#Sta/Elev= 22
       0  835.25     9.7   830.7    19.4  828.16    29.2  826.96    77.8  822.79
   116.7  819.93   126.4  819.26   134.9  818.83   145.8  818.68   149.9  818.79
   155.5  818.94   165.3  819.59   194.4  821.87   204.2  823.07   213.9  824.72
   223.6  827.28   233.3  831.19   252.8  840.94   262.5  845.25   272.2  849.21
   281.9  852.96   291.6  856.51
#Mann= 3 , 0 , 0
       0     .06       0   134.9    .045       0   149.9     .08       0
Bank Sta=134.9,149.9
XS Rating Curve= 0 ,0
Exp/Cntr=0.3,0.1

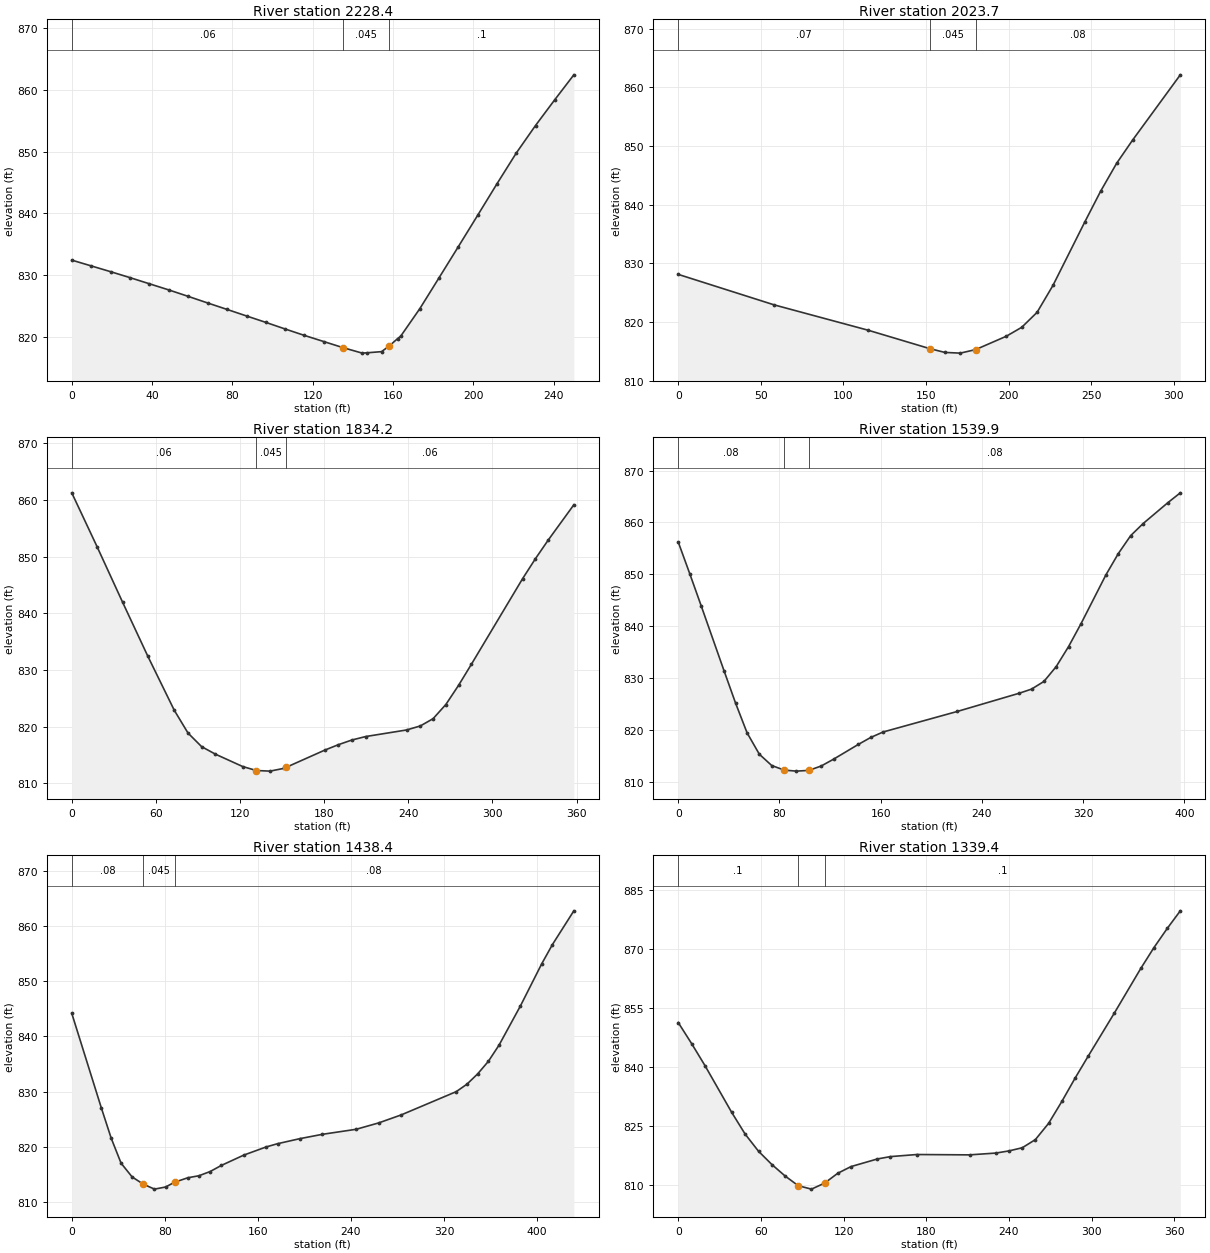
Type RM Length L Ch R = 1 ,2228.4  ,191.7,204.7,217.7
XS GIS Cut Line= 3
     1630152.386      348434.318     1630060.155      348463.615
     1629922.351      348530.889
#Sta/Elev= 30
       0  832.42     9.7  831.48    19.4  830.54      29  829.58    38.7  828.58
    48.4  827.58    58.1  826.53    67.7  825.47    77.4  824.42    87.1  823.36
    96.8  822.31   106.4  821.24   115.9  820.21   125.5  819.22   135.1  818.23
   144.7  817.34   147.3   817.4   154.3  817.58   158.1  818.49   162.3  819.69
   163.9  820.11   173.4  824.56     183  829.58   192.6  834.62   202.2  839.69
   211.8  844.79   221.4  849.77     231  854.24   240.5  858.38   250.1  862.46
#Mann= 3 , 0 , 0
       0     .06       0   135.1    .045       0   158.1      .1       0
Bank Sta=135.1,158.1
XS Rating Curve= 0 ,0
Exp/Cntr=0.3,0.1

Type RM Length L Ch R = 1 ,2023.7  ,196.3,189.5,182.9
XS GIS Cut Line= 4
     1630112.238      348333.407     1630029.773      348305.195
      1629900.65      348290.004     1629826.865      348335.577
#Sta/Elev= 16
       0  828.11    58.1  822.91     115  818.59   152.2  815.46   161.4  814.81
   170.7  814.69     180  815.29   198.6  817.57   207.9  819.09   217.2  821.64
   226.8  826.22   246.1  837.05   255.7   842.3   265.4  847.06     275  850.99
   303.9  862.12
#Mann= 3 , 0 , 0
       0     .07       0   152.2    .045       0     180     .08       0
Bank Sta=152.2,180
XS Rating Curve= 0 ,0
Exp/Cntr=0.3,0.1

Type RM Length L Ch R = 1 ,1834.2  ,303.9,294.3,284.5
XS GIS Cut Line= 4
     1630079.686      348054.544     1630029.773      348093.606
     1629847.481      348126.159     1629756.336      348186.922
#Sta/Elev= 27
       0  861.25    18.1  851.72    36.2  841.98    54.3   832.4    73.1   822.9
    82.9  818.88    92.6  816.48   102.4  815.16   121.9  812.97   131.6  812.27
   141.4  812.16   151.1  812.64     153  812.84   180.3  815.85   190.1  816.82
   199.8  817.65   209.6  818.26   238.8  819.42   248.6  820.13   257.7  821.41
   266.8  823.91   275.9   827.3   285.1  831.04   321.6  846.13   330.7  849.63
   339.8  852.91   358.1  859.14
#Mann= 3 , 0 , 0
       0     .06       0   131.6    .045       0     153     .06       0
Bank Sta=131.6,153
XS Rating Curve= 0 ,0
Exp/Cntr=0.3,0.1

Type RM Length L Ch R = 1 ,1539.9  ,95,101.5,107.9
XS GIS Cut Line= 4
     1629948.393      347786.532     1629899.565      347810.403
     1629697.742      347948.207     1629656.509      348037.183
#Sta/Elev= 29
       0  856.21     9.1   850.1    18.1  843.93    36.2  831.37    45.3  825.14
    54.4   819.4    64.1  815.27    73.9  813.09    83.7  812.21    93.4  812.01
   103.2  812.15     113     813   122.8  814.32   142.3  817.16   152.1   818.5
   161.9  819.56   220.5  823.52   269.4  827.03   279.2  827.83     289  829.31
   298.7  832.17   308.5  836.04   318.4  840.49     338  849.87   347.8  853.98
   357.6  857.45   367.4  859.77     387  863.81   396.8   865.7
#Mann= 3 , 0 , 0
       0     .08       0    83.7    .045       0   103.2     .08       0
Bank Sta=83.7,103.2
XS Rating Curve= 0 ,0
Exp/Cntr=0.3,0.1

Type RM Length L Ch R = 1 ,1438.4  ,90.8,99,107.2
XS GIS Cut Line= 5
     1629910.415      347716.002     1629869.183      347725.768
     1629796.483      347749.639       1629671.7      347897.209
     1629635.893      348011.141
#Sta/Elev= 30
       0  844.19    25.4  827.09    33.9  821.59    42.4  817.07    51.9  814.58
    61.5  813.28    71.1  812.38    80.6  812.76    88.4  813.63    99.8  814.44
   109.3   814.8   118.9  815.56   128.6  816.67   147.9  818.54   167.2  820.02
   176.9   820.6   196.2  821.52   215.5   822.3   244.5  823.21   263.8  824.36
   283.2  825.81   330.5  830.02   339.7  831.37   348.9  833.23   358.1   835.5
   367.3  838.44   385.6   845.5     404  853.16   413.2  856.64   431.6  862.74
#Mann= 3 , 0 , 0
       0     .08       0    61.5    .045       0    88.4     .08       0
Bank Sta=61.5,88.4
XS Rating Curve= 0 ,0
Exp/Cntr=0.3,0.1

Type RM Length L Ch R = 1 ,1339.4  ,95.8,72.5,49.1
XS GIS Cut Line= 3
     1629910.415      347622.686     1629845.311      347642.218
     1629549.087      347630.282
#Sta/Elev= 30
       0  851.26     9.7  845.93    19.4  840.34    38.8  828.47    48.6  822.94
    58.3   818.6      68  815.23    77.5  812.35    87.1  809.87    96.7     809
   106.2  810.52   115.8  813.03   125.4  814.72   144.5  816.65     154  817.25
   173.2  817.78   211.4  817.69   230.6  818.15   240.1   818.7   249.7   819.5
   259.2  821.56   268.8  825.68   278.4  831.23   287.9  837.08   297.5  842.71
   316.6  853.71   335.7  864.98   345.3  870.29   354.9  875.13   364.4   879.6
#Mann= 3 , 0 , 0
       0      .1       0    87.1    .045       0   106.2      .1       0
Bank Sta=87.1,106.2
XS Rating Curve= 0 ,0
Exp/Cntr=0.3,0.1