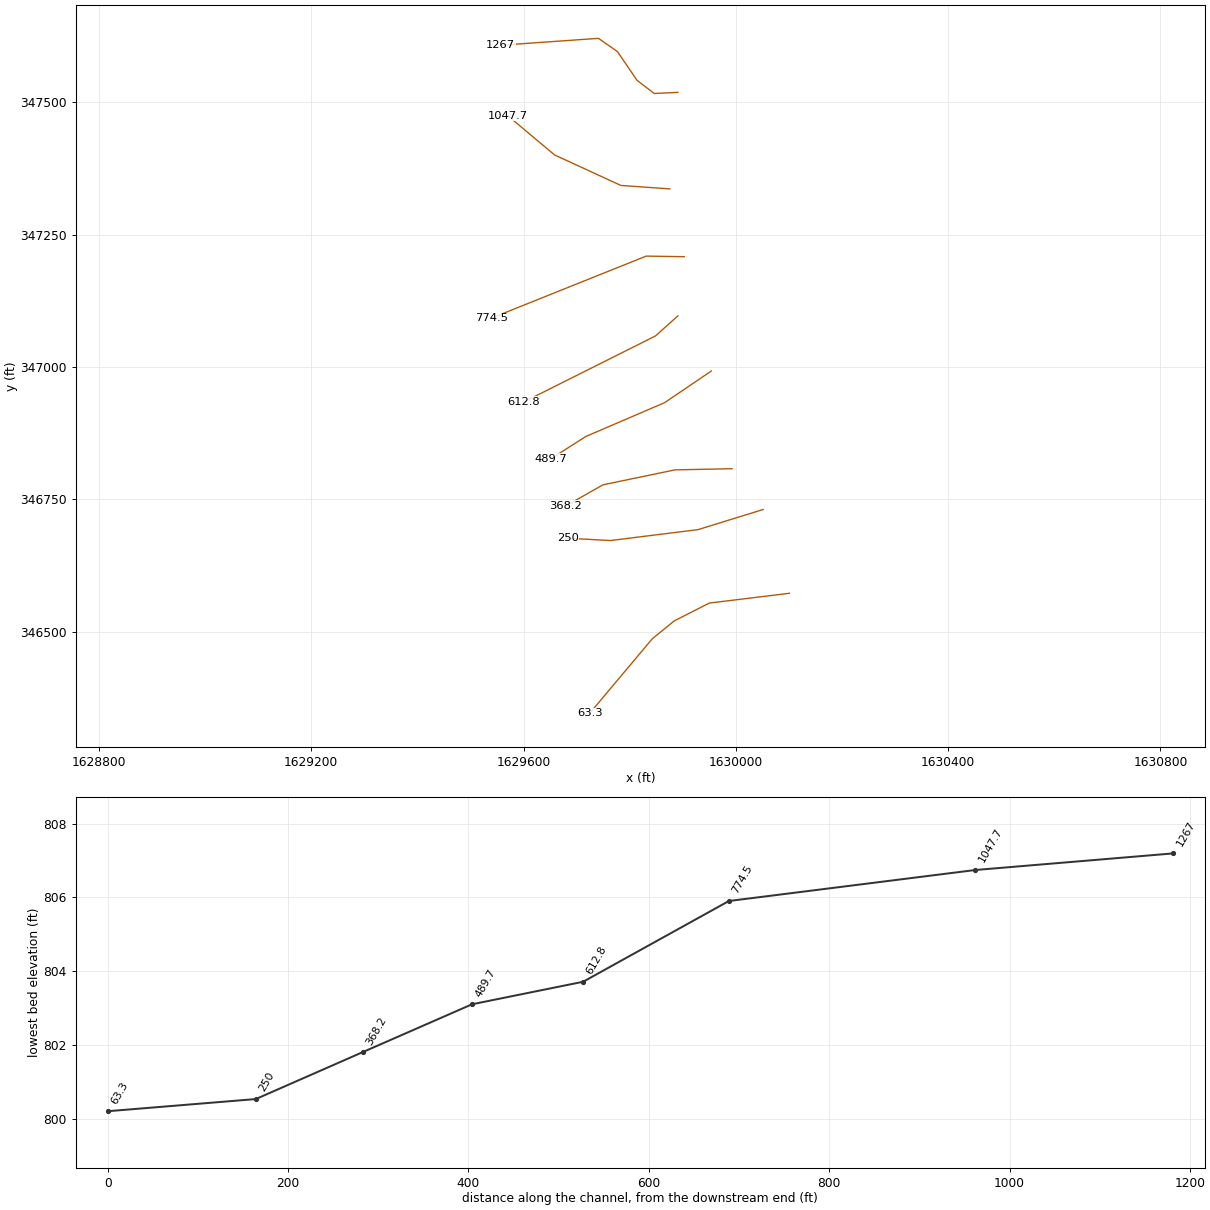
HEC-RAS study STKPOLRN.prj: STKPOLRN

--- STKPOLRN.g02 (geometry) --- (continued)

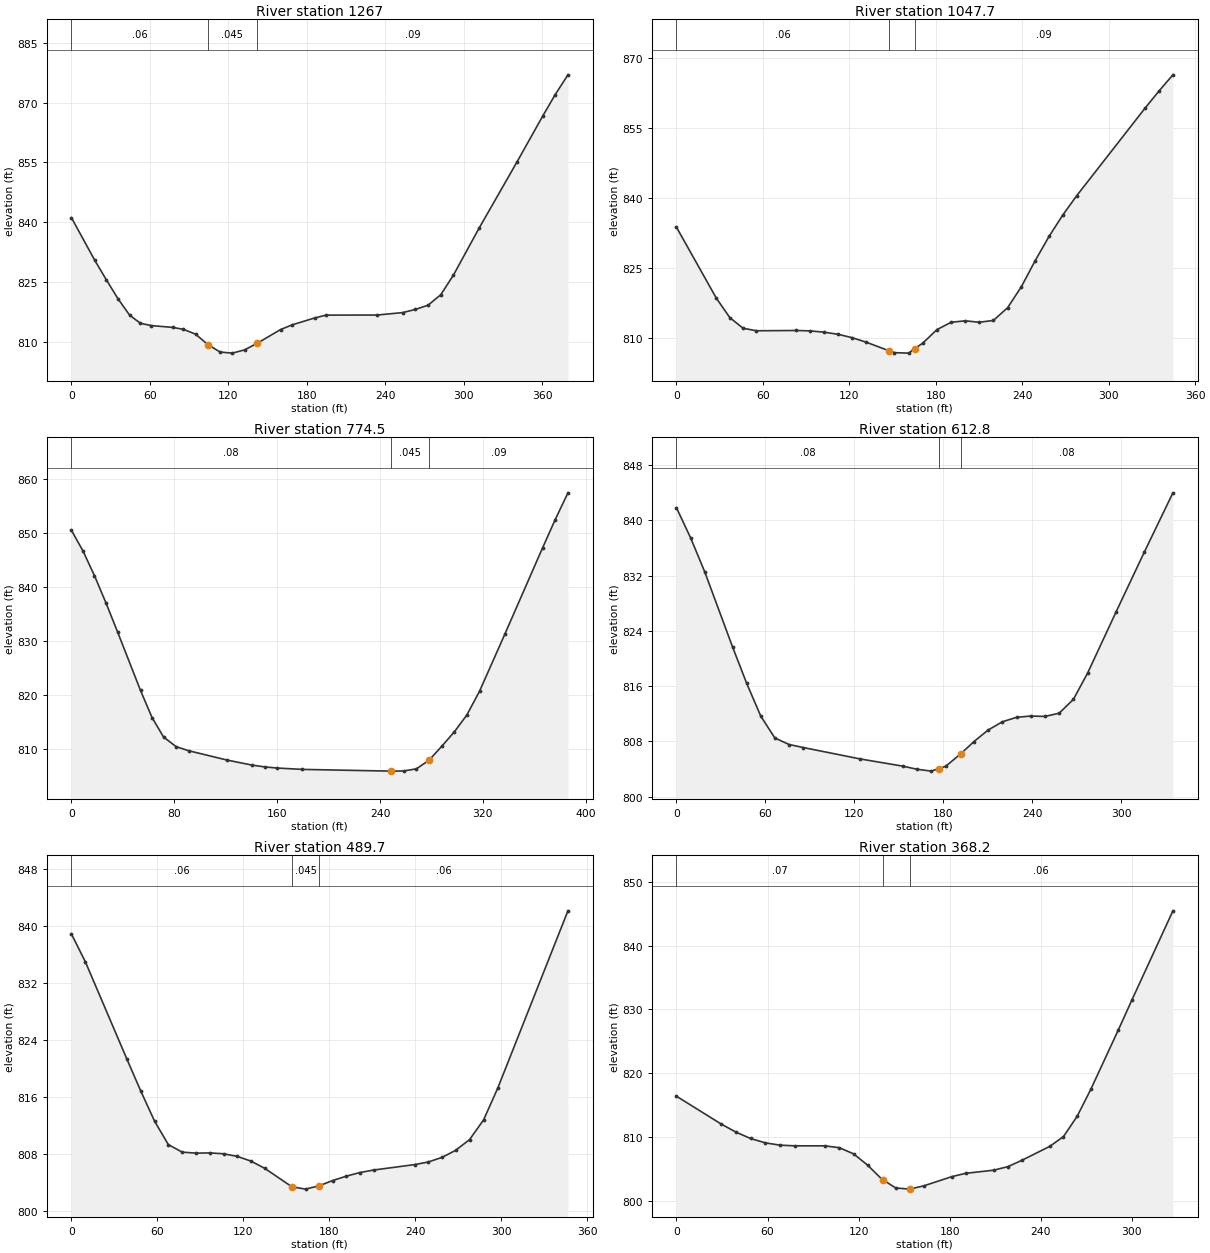
Type RM Length L Ch R = 1 ,1267    ,207,219.3,231.5
XS GIS Cut Line= 6
     1629890.884       347518.52     1629846.396      347516.349
     1629813.844      347541.306     1629776.952       347595.56
     1629741.145      347620.516     1629556.683      347607.495
#Sta/Elev= 30
       0  841.13    17.8  830.46    26.7  825.55    35.6  820.81    44.5  816.69
    52.7  814.68      61   814.1    77.4  813.64    85.6  813.15    94.9  811.95
   104.3  809.33   113.7  807.46     123  807.19   132.4  808.01   141.8  809.61
   159.9   813.1   168.6  814.26   186.1  816.02   194.8  816.72   233.7  816.74
   253.2  817.35   262.9  818.13   272.7   819.2   282.4  821.82   292.1  826.74
   311.6  838.44   340.8  855.16   360.3  866.56     370  872.02   379.7  876.96
#Mann= 3 , 0 , 0
       0     .06       0   104.3    .045       0   141.8     .09       0
Bank Sta=104.3,141.8
XS Rating Curve= 0 ,0
Exp/Cntr=0.3,0.1

Type RM Length L Ch R = 1 ,1047.7  ,254.3,273.2,292
XS GIS Cut Line= 4
     1629875.693      347336.228     1629783.462      347342.738
     1629658.679      347400.247     1629570.789      347474.032
#Sta/Elev= 30
       0  833.78    27.7  818.53      37  814.38    46.2  812.09    55.5  811.54
    83.2   811.6    92.5  811.52   102.3  811.24   112.1  810.79   121.9  810.06
   131.7  809.09   147.6  807.24   151.3  806.84   161.2  806.74  165.23  807.68
     171  808.89   180.8  811.79   190.6  813.35   200.4  813.68   210.2  813.37
     220  813.76   229.9  816.51   239.4  820.99     249  826.59   258.6  831.79
   268.1  836.36   277.7  840.49   325.5  859.43     335  863.04   344.6  866.49
#Mann= 3 , 0 , 0
       0     .06       0   147.6    .045       0  165.23     .09       0
Bank Sta=147.6,165.23
XS Rating Curve= 0 ,0
Exp/Cntr=0.3,0.1

Type RM Length L Ch R = 1 ,774.5   ,159.8,161.7,163.5
XS GIS Cut Line= 3
      1629902.82       347208.19     1629831.205      347209.275
     1629539.322      347092.087
#Sta/Elev= 27
       0   850.5       9  846.66    17.9   842.1    26.9  837.02    35.8  831.72
    53.7  820.84    62.7  815.81    71.6  812.23    81.4  810.43    91.3  809.67
   120.8  807.96   140.4  807.02   150.3  806.68   160.1  806.47   179.7  806.22
   248.6   805.9   258.4  805.93   268.2  806.32     278  807.88   287.9  810.47
   297.7  813.14   307.5  816.28   317.4  820.69     337  831.22   366.5  847.28
   376.3   852.5   386.2  857.46
#Mann= 3 , 0 , 0
       0     .08       0   248.6    .045       0     278     .09       0
Bank Sta=248.6,278
XS Rating Curve= 0 ,0
Exp/Cntr=0.3,0.1

Type RM Length L Ch R = 1 ,612.8   ,124.8,123.1,121.6
XS GIS Cut Line= 3
     1629890.884      347096.428     1629848.567       347058.45
     1629600.086      346933.667
#Sta/Elev= 28
       0   841.8     9.5  837.47      19  832.57    37.9  821.64    47.4  816.39
    56.9  811.65    66.4   808.5      76  807.56    85.6  807.12     124  805.47
   152.7  804.43   162.3  803.98   171.9  803.71   176.8  804.06   181.5  804.39
   191.8  806.22   200.7  807.99   210.3  809.66   219.9  810.85   229.4  811.49
     239  811.68   248.6  811.62   258.2  812.09   267.8   814.1   277.4  817.91
   296.6  826.76   315.7  835.43   334.9  843.96
#Mann= 3 , 0 , 0
       0     .08       0   176.8    .045       0   191.8     .08       0
Bank Sta=176.8,191.8
XS Rating Curve= 0 ,0
Exp/Cntr=0.3,0.1

Type RM Length L Ch R = 1 ,489.7   ,125.8,121.5,116.5
XS GIS Cut Line= 4
     1629953.818      346992.261     1629865.928      346932.582
     1629717.273      346868.563     1629651.084      346826.245
#Sta/Elev= 28
       0  838.88     9.7  834.98    38.6  821.38    48.3  816.89      58  812.64
    67.6  809.35    77.3  808.29    86.9  808.15    96.6  808.18   106.2  808.06
   115.8  807.69   125.3  807.03   134.8  806.03   153.8  803.44   163.4   803.1
   172.9  803.57   182.4  804.31   191.9  804.92   201.4  805.43     211  805.78
   239.5  806.54     249   806.9   258.6  807.55   268.1  808.53   277.9  810.04
   287.7  812.81   297.6  817.27   346.6  842.14
#Mann= 3 , 0 , 0
       0     .06       0   153.8    .045       0   172.9     .06       0
Bank Sta=153.8,172.9
XS Rating Curve= 0 ,0
Exp/Cntr=0.3,0.1

Type RM Length L Ch R = 1 ,368.2   ,119.6,118.3,116.4
XS GIS Cut Line= 4
     1629992.881      346807.799     1629885.459      346805.629
     1629749.825      346777.417     1629679.296       346737.27
#Sta/Elev= 28
       0  816.37    29.3  812.03    39.1  810.75    48.8  809.74    58.6  809.05
    68.4  808.69    78.1  808.59    97.7  808.59   107.4  808.29   116.7  807.33
   125.9  805.57   135.2  803.39   136.2  803.24   144.4  801.99   153.6   801.8
   162.9  802.31   181.3  803.75   190.6  804.28     209  804.77   218.3  805.32
   227.5  806.31     246  808.51     255  810.04     264  813.22     273  817.45
   291.1  826.74   300.1  831.47   327.1  845.44
#Mann= 3 , 0 , 0
       0     .07       0   136.2    .045       0   153.6     .06       0
Bank Sta=136.2,153.6
XS Rating Curve= 0 ,0
Exp/Cntr=0.3,0.1

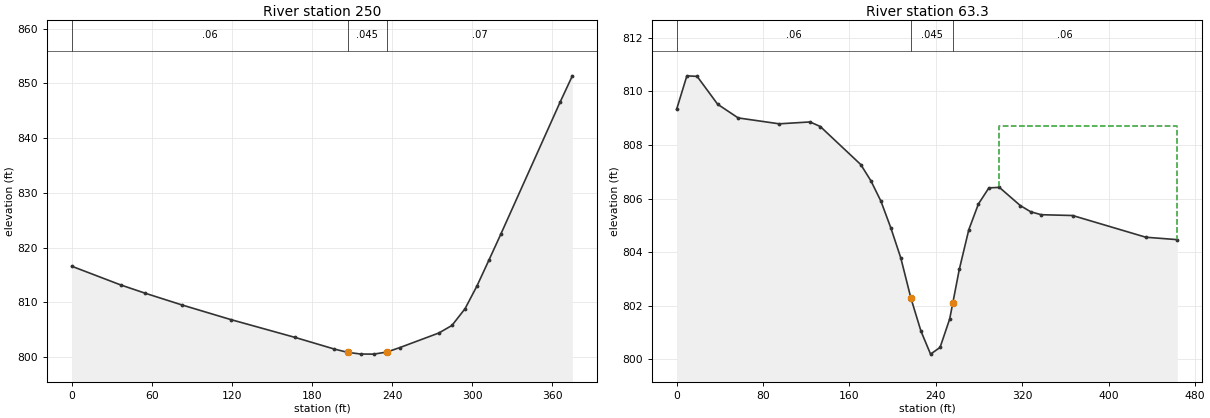
Type RM Length L Ch R = 1 ,250     ,157.8,164.3,171.2
XS GIS Cut Line= 4
     1630051.475      346730.759     1629928.862      346692.782
     1629763.931      346672.165     1629683.636      346676.506
#Sta/Elev= 20
       0  816.59    36.7  813.17      55  811.66    82.5  809.52   119.2  806.84
   167.5  803.57   196.8  801.45   206.6  800.86   216.4  800.55   226.1  800.53
   235.9   800.9   245.7  801.72     275  804.39   284.8  805.77   294.6  808.82
   303.5  812.96   312.4  817.65   321.4  822.44     366  846.66     375  851.37
#Mann= 3 , 0 , 0
       0     .06       0   206.6    .045       0   235.9     .07       0
Bank Sta=206.6,235.9
XS Rating Curve= 0 ,0
Exp/Cntr=0.3,0.1

Type RM Length L Ch R = 1 ,63.3    ,60.1,63.3,66.5
XS GIS Cut Line= 5
     1630101.062      346572.556     1629950.238       346554.11
     1629884.048      346520.473     1629842.816      346486.836
     1629724.543      346345.777
#Sta/Elev= 30
       0  809.33     9.5  810.58      19  810.56      38  809.52      57  809.01
      95  808.79   123.5  808.86     133  808.69   170.5  807.27   179.8  806.67
   189.1  805.91   198.4   804.9   207.6  803.78   216.9  802.29   226.2  801.06
   235.1   800.2   243.9  800.45   252.8  801.51   255.7  802.11   261.7  803.36
   270.5  804.84   279.4   805.8   289.1   806.4   298.8  806.42   318.2  805.74
   327.8  805.51   337.5   805.4   366.6  805.37   434.4  804.56   463.5  804.47
#Mann= 3 , 0 , 0
       0     .06       0   216.9    .045       0   255.7     .06       0
#XS Ineff= 2 , 0
                          298.51           808.7
Permanent Ineff=
       F       F
Bank Sta=216.9,255.7
XS Rating Curve= 0 ,0
Exp/Cntr=0.3,0.1